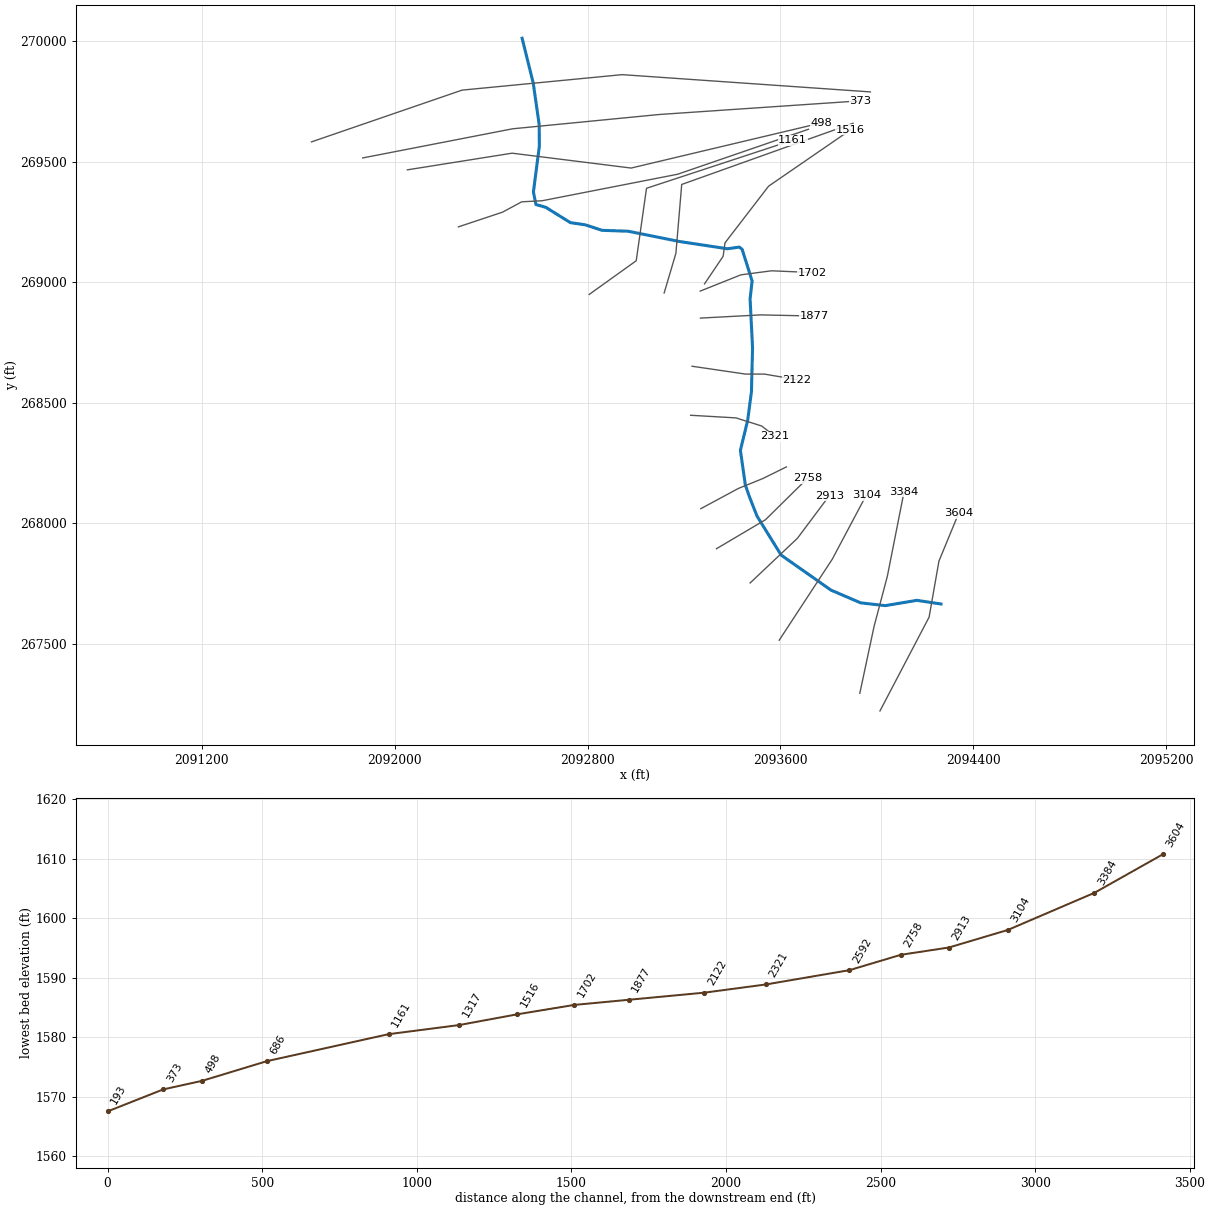
--- GRBRRVTR1.prj (project) ---

Proj Title=GRBRRVTR1
Current Plan=p01
Default Exp/Contr=0,0
English Units
Geom File=g01
Flow File=f01
Plan File=p01
BEGIN DESCRIPTION:
Stream Name- Greenbrier River Tributary 1
Flood Zone: Zone A
Greenbrier County, WV
County-Wide Study
WVDHSEM-2018-3, Flood Risk Project
HEC-RAS Version: 5.0.7
General Notes:
For the Hydrology Regression was used.
END DESCRIPTION:
DSS Export Rating Curves= 0
DSS Export Rating Curve Sorted= 0
DSS Export Volume Flow Curves= 0
DXF Filename=..\..\..\H1\Remaining\splitted_models\GRBRRVTR1\GRBRRVTR1.
DXF OffsetX= 0
DXF OffsetY= 0
DXF ScaleX= 0
DXF ScaleY= 0

--- GRBRRVTR1.p01 (plan) ---

Plan Title=Floodplain
Program Version=5.07
Short Identifier=Floodplain
Geom File=g01
Flow File=f01
Subcritical Flow
K Sum by GR= 0
Std Step Tol= 0.01
Critical Tol= 0.01
Num of Std Step Trials= 20
Max Error Tol= 0.3
Flow Tol Ratio= 0.001
Split Flow NTrial= 30
Split Flow Tol= 0.02
Split Flow Ratio= 0.02
Log Output Level= 0
Friction Slope Method= 1
Unsteady Friction Slope Method= 2
Unsteady Bridges Friction Slope Method= 1
Parabolic Critical Depth
Global Vel Dist= 0 , 0 , 0
Global Log Level= 0
CheckData=True
Encroach Param=-1 ,0,0, 0
Mapping Interval=1HOUR
Computation Time Step Use Courant=        0
Computation Time Step Use Time Series=    0
Computation Time Step Count To Double=0
Computation Time Step Max Doubling=0
Computation Time Step Max Halving=0
Computation Time Step Residence Courant=0
Run HTab= 0
Run UNet= 0
Run Sediment= 0
Run PostProcess= 0
Run WQNet= 0
Run RASMapper= 0
UNET Theta= 0
UNET Theta Warmup= 0
UNET ZTol= 0
UNET ZSATol= 0
UNET MxIter= 0
UNET Max Iter WO Improvement= 0
UNET MaxInSteps= 0
UNET DtIC= 0
UNET DtMin= 0
UNET MaxCRTS= 0
UNET WFStab= 0
UNET SFStab= 0
UNET WFX= 1
UNET SFX= 1
UNET 1D Methodology=Finite Difference
UNET DSS MLevel= 1
UNET Pardiso=0
UNET DZMax Abort= 0
UNET Use Existing IB Tables= 0
UNET Froude Reduction=False
UNET Froude Limit= 0
UNET Froude Power= 0
UNET D1 Cores= 0
UNET D2 Coriolis=0
UNET D2 Cores= 0
UNET D2 Theta= 1
UNET D2 Theta Warmup= 1
UNET D2 Z Tol= 0.01
UNET D2 Volume Tol= 0.01
UNET D2 Max Iterations= 20
UNET D2 Equation= 0
UNET D2 RampUpFraction=0.1
UNET D2 TimeSlices= 1
UNET D2 BCVolumeCheck=0
UNET D1D2 MaxIter= 0
UNET D1D2 ZTol=0.01
UNET D1D2 QTol=0.1
UNET D1D2 MinQTol=1
Write IC File= 0
Write IC File at Fixed DateTime=0
Write IC File at Sim End=0
Echo Input=False
Echo Parameters=False
Echo Output=False
Write Detailed= 0
HDF Write Warmup=0
HDF Write Time Slices=0
HDF Flush=0
HDF Face Node Velocities=0
HDF Compression= 1
HDF Chunk Size= 1
HDF Spatial Parts= 1
HDF Use Max Rows=0
HDF Fixed Rows= 1
Calibration Method= 0
Calibration Iterations= 20
Calibration Max Change=0.05
Calibration Tolerance=0.2
Calibration Maximum=1.5
Calibration Minimum=0.5
Calibration Optimization Method= 1
WQ AD Non Conservative
WQ ULTIMATE=-1
WQ Max Comp Step=1HOUR
WQ Output Interval=15MIN
WQ Output Selected Increments= 0
WQ Output face flow=0
WQ Output face velocity=0
WQ Output face area=0
WQ Output face dispersion=0
WQ Output cell volume=0
WQ Output cell surface area=0
WQ Output cell continuity=0
WQ Output cumulative cell continuity=0
WQ Output face conc=0
WQ Output face dconc_dx=0
WQ Output face courant=0
WQ Output face peclet=0
WQ Output face adv mass=0
WQ Output face disp mass=0
WQ Output cell mass=0
WQ Output cell source sink temp=0
WQ Output nsm pathways=0
WQ Output nsm derived pathways=0
WQ Output MaxMinRange=-1
WQ Daily Max Min Mean=-1
WQ Daily Range=0
WQ Daily Time=0
WQ Create Restart=0
WQ Fixed Restart=0
WQ System Summary=0
WQ Write To DSS=0
WQ Use Fixed Temperature=0
Sorting and Armoring Iterations= 10
XS Update Threshold= 0.02
Bed Roughness Predictor= 0
Hydraulics Update Threshold= 0.02
Energy Slope Method= 1
Volume Change Method= 1
Sediment Retention Method= 0
XS Weighting Method= 0
Number of US Weighted Cross Sections= 1
Number of DS Weighted Cross Sections= 1
Upstream XS Weight=0
Main XS Weight=1
Downstream XS Weight=0
Number of DS XS's Weighted with US Boundary= 1
Upstream Boundary Weight= 1
Weight of XSs Associated with US Boundary= 0
Number of US XS's Weighted with DS Boundary= 1
Downstream Boundary Weight= 0.5
Weight of XSs Associated with DS Boundary= 0.5
Percentile Method= 0
Sediment Output Level= 3
Mass or Volume Output= 0
Output Increment Type= 1
Profile and TS Output Increment= 1
XS Output Flag= 0
XS Output Increment= 10
Write Gradation File= 0
Read Gradation Hotstart= 0
Write HDF5 File= 1
Write Binary Output= 1
Write DSS Sediment File= 0
SV Curve= 0
Specific Gage Flag= 0

--- GRBRRVTR1.f01 (steady flow) ---

Flow Title=Flow
Program Version=5.07
Number of Profiles= 6
Profile Names=f1p,f10p,f4p,f2p,f02p,f1pplus
River Rch & RM=GRBRRVTR1,Main            ,3604
    2910    1640    2110    2500    3940    4300
Boundary for River Rch & Prof#=ANGLINSCK,Main            , 1
Up Type= 0
Dn Type= 3
Dn Slope=0.00963
Boundary for River Rch & Prof#=ANGLINSCK,Main            , 2
Up Type= 0
Dn Type= 3
Dn Slope=0.00963
Boundary for River Rch & Prof#=ANGLINSCK,Main            , 3
Up Type= 0
Dn Type= 3
Dn Slope=0.00963
Boundary for River Rch & Prof#=ANGLINSCK,Main            , 4
Up Type= 0
Dn Type= 3
Dn Slope=0.00963
Boundary for River Rch & Prof#=ANGLINSCK,Main            , 5
Up Type= 0
Dn Type= 3
Dn Slope=0.00963
Boundary for River Rch & Prof#=ANGLINSCK,Main            , 6
Up Type= 0
Dn Type= 3
Dn Slope=0.00963
Boundary for River Rch & Prof#=GRBRRVTR1,Main            , 1
Up Type= 0
Dn Type= 3
Dn Slope=0.01784
Boundary for River Rch & Prof#=GRBRRVTR1,Main            , 2
Up Type= 0
Dn Type= 3
Dn Slope=0.01784
Boundary for River Rch & Prof#=GRBRRVTR1,Main            , 3
Up Type= 0
Dn Type= 3
Dn Slope=0.01784
Boundary for River Rch & Prof#=GRBRRVTR1,Main            , 4
Up Type= 0
Dn Type= 3
Dn Slope=0.01784
Boundary for River Rch & Prof#=GRBRRVTR1,Main            , 5
Up Type= 0
Dn Type= 3
Dn Slope=0.01784
Boundary for River Rch & Prof#=GRBRRVTR1,Main            , 6
Up Type= 0
Dn Type= 3
Dn Slope=0.01784
Boundary for River Rch & Prof#=GRBRRVTR2,Main            , 1
Up Type= 0
Dn Type= 3
Dn Slope=0.01456
Boundary for River Rch & Prof#=GRBRRVTR2,Main            , 2
Up Type= 0
Dn Type= 3
Dn Slope=0.01456
Boundary for River Rch & Prof#=GRBRRVTR2,Main            , 3
Up Type= 0
Dn Type= 3
Dn Slope=0.01456
Boundary for River Rch & Prof#=GRBRRVTR2,Main            , 4
Up Type= 0
Dn Type= 3
Dn Slope=0.01456
Boundary for River Rch & Prof#=GRBRRVTR2,Main            , 5
Up Type= 0
Dn Type= 3
Dn Slope=0.01456
Boundary for River Rch & Prof#=GRBRRVTR2,Main            , 6
Up Type= 0
Dn Type= 3
Dn Slope=0.01456
Boundary for River Rch & Prof#=GRBRRVTR4,Main            , 1
Up Type= 0
Dn Type= 3
Dn Slope=0.00727
Boundary for River Rch & Prof#=GRBRRVTR4,Main            , 2
Up Type= 0
Dn Type= 3
Dn Slope=0.00727
Boundary for River Rch & Prof#=GRBRRVTR4,Main            , 3
Up Type= 0
Dn Type= 3
Dn Slope=0.00727
Boundary for River Rch & Prof#=GRBRRVTR4,Main            , 4
Up Type= 0
Dn Type= 3
Dn Slope=0.00727
Boundary for River Rch & Prof#=GRBRRVTR4,Main            , 5
Up Type= 0
Dn Type= 3
Dn Slope=0.00727
Boundary for River Rch & Prof#=GRBRRVTR4,Main            , 6
Up Type= 0
Dn Type= 3
Dn Slope=0.00727
Boundary for River Rch & Prof#=HOMINYCK,Main            , 1
Up Type= 0
Dn Type= 3
Dn Slope=0.02963
Boundary for River Rch & Prof#=HOMINYCK,Main            , 2
Up Type= 0
Dn Type= 3
Dn Slope=0.02963
Boundary for River Rch & Prof#=HOMINYCK,Main            , 3
Up Type= 0
Dn Type= 3
Dn Slope=0.02963
Boundary for River Rch & Prof#=HOMINYCK,Main            , 4
Up Type= 0
Dn Type= 3
Dn Slope=0.02963
Boundary for River Rch & Prof#=HOMINYCK,Main            , 5
Up Type= 0
Dn Type= 3
Dn Slope=0.02963
Boundary for River Rch & Prof#=HOMINYCK,Main            , 6
Up Type= 0
Dn Type= 3
Dn Slope=0.02963
Boundary for River Rch & Prof#=HOWARDCK,Main            , 1
Up Type= 0
Dn Type= 1
Dn Known WS=1885.77
Boundary for River Rch & Prof#=HOWARDCK,Main            , 2
Up Type= 0
Dn Type= 1
Dn Known WS=1884.59
Boundary for River Rch & Prof#=HOWARDCK,Main            , 3
Up Type= 0
Dn Type= 1
Dn Known WS=1885.21
Boundary for River Rch & Prof#=HOWARDCK,Main            , 4
Up Type= 0
Dn Type= 1
Dn Known WS=1885.53
Boundary for River Rch & Prof#=HOWARDCK,Main            , 5
Up Type= 0
Dn Type= 1
Dn Known WS=1886.34
Boundary for River Rch & Prof#=HOWARDCK,Main            , 6
Up Type= 0
Dn Type= 1
Dn Known WS=1886.04
Boundary for River Rch & Prof#=JERCHODFT,Main            , 1
Up Type= 0
Dn Type= 3
Dn Slope=0.00689
Boundary for River Rch & Prof#=JERCHODFT,Main            , 2
Up Type= 0
Dn Type= 3
Dn Slope=0.00689
Boundary for River Rch & Prof#=JERCHODFT,Main            , 3
Up Type= 0
Dn Type= 3
Dn Slope=0.00689
Boundary for River Rch & Prof#=JERCHODFT,Main            , 4
Up Type= 0
Dn Type= 3
Dn Slope=0.00689
Boundary for River Rch & Prof#=JERCHODFT,Main            , 5
Up Type= 0
Dn Type= 3
Dn Slope=0.00689
Boundary for River Rch & Prof#=JERCHODFT,Main            , 6
Up Type= 0
Dn Type= 3
Dn Slope=0.00689
Boundary for River Rch & Prof#=JERCHODFTT1,Main            , 1
Up Type= 0
Dn Type= 3
Dn Slope=0.01752
Boundary for River Rch & Prof#=JERCHODFTT1,Main            , 2
Up Type= 0
Dn Type= 3
Dn Slope=0.01752
Boundary for River Rch & Prof#=JERCHODFTT1,Main            , 3
Up Type= 0
Dn Type= 3
Dn Slope=0.01752
Boundary for River Rch & Prof#=JERCHODFTT1,Main            , 4
Up Type= 0
Dn Type= 3
Dn Slope=0.01752
Boundary for River Rch & Prof#=JERCHODFTT1,Main            , 5
Up Type= 0
Dn Type= 3
Dn Slope=0.01752
Boundary for River Rch & Prof#=JERCHODFTT1,Main            , 6
Up Type= 0
Dn Type= 3
Dn Slope=0.01752
Boundary for River Rch & Prof#=LITTLECK2,Main            , 1
Up Type= 0
Dn Type= 3
Dn Slope=0.00092
Boundary for River Rch & Prof#=LITTLECK2,Main            , 2
Up Type= 0
Dn Type= 3
Dn Slope=0.00092
Boundary for River Rch & Prof#=LITTLECK2,Main            , 3
Up Type= 0
Dn Type= 3
Dn Slope=0.00092
Boundary for River Rch & Prof#=LITTLECK2,Main            , 4
Up Type= 0
Dn Type= 3
Dn Slope=0.00092
Boundary for River Rch & Prof#=LITTLECK2,Main            , 5
Up Type= 0
Dn Type= 3
Dn Slope=0.00092
Boundary for River Rch & Prof#=LITTLECK2,Main            , 6
Up Type= 0
Dn Type= 3
Dn Slope=0.00092
Boundary for River Rch & Prof#=SLPHRLCKRN,Main            , 1
Up Type= 0
Dn Type= 3
Dn Slope=0.01995
Boundary for River Rch & Prof#=SLPHRLCKRN,Main            , 2
Up Type= 0
Dn Type= 3
Dn Slope=0.01995
Boundary for River Rch & Prof#=SLPHRLCKRN,Main            , 3
Up Type= 0
Dn Type= 3
Dn Slope=0.01995
Boundary for River Rch & Prof#=SLPHRLCKRN,Main            , 4
Up Type= 0
Dn Type= 3
Dn Slope=0.01995
Boundary for River Rch & Prof#=SLPHRLCKRN,Main            , 5
Up Type= 0
Dn Type= 3
Dn Slope=0.01995
Boundary for River Rch & Prof#=SLPHRLCKRN,Main            , 6
Up Type= 0
Dn Type= 3
Dn Slope=0.01995
Boundary for River Rch & Prof#=SLSHLCKRN,Main            , 1
Up Type= 0
Dn Type= 3
Dn Slope=0.01085
Boundary for River Rch & Prof#=SLSHLCKRN,Main            , 2
Up Type= 0
Dn Type= 3
Dn Slope=0.01085
Boundary for River Rch & Prof#=SLSHLCKRN,Main            , 3
Up Type= 0
Dn Type= 3
Dn Slope=0.01085
Boundary for River Rch & Prof#=SLSHLCKRN,Main            , 4
Up Type= 0
Dn Type= 3
Dn Slope=0.01085
Boundary for River Rch & Prof#=SLSHLCKRN,Main            , 5
Up Type= 0
Dn Type= 3
Dn Slope=0.01085
Boundary for River Rch & Prof#=SLSHLCKRN,Main            , 6
Up Type= 0
Dn Type= 3
Dn Slope=0.01085
Boundary for River Rch & Prof#=YOUNGSCK,Main            , 1
Up Type= 0
Dn Type= 3
Dn Slope=0.02815
Boundary for River Rch & Prof#=YOUNGSCK,Main            , 2
Up Type= 0
Dn Type= 3
Dn Slope=0.02815
Boundary for River Rch & Prof#=YOUNGSCK,Main            , 3
Up Type= 0
Dn Type= 3
Dn Slope=0.02815
Boundary for River Rch & Prof#=YOUNGSCK,Main            , 4
Up Type= 0
Dn Type= 3
Dn Slope=0.02815
Boundary for River Rch & Prof#=YOUNGSCK,Main            , 5
Up Type= 0
Dn Type= 3
Dn Slope=0.02815
Boundary for River Rch & Prof#=YOUNGSCK,Main            , 6
Up Type= 0
Dn Type= 3
Dn Slope=0.02815
DSS Import GetInterval= 0
DSS Import GetPeak= 0
DSS Import FillOption= 0

--- GRBRRVTR1.g01 (geometry) ---

Geom Title=Geometry
Program Version=5.07

River Reach=GRBRRVTR1       ,Main
Reach XY= 30
     2094265.777      267664.753     2094165.357      267679.958
     2094034.641      267657.988     2093932.381      267669.535
     2093809.194      267722.6642093603.05487467267867.601797059
 2093503.2994896268028.7043747112093469.92717101268113.418721915
2093454.52456242268158.3429969472093433.98775098268302.100677052
     2093464.169      268427.023     2093479.737      268544.868
     2093484.403      268727.213     2093474.201      268930.041
     2093482.463      269004.901      2093441.24        269136.1
     2093429.149      269145.473     2093379.983        269138.5
     2093178.374      269168.978     2092969.091      269211.158
      2092860.45      269214.934     2092790.892      269237.743
     2092729.063      269246.856     2092626.646      269310.532
     2092585.869      269322.032     2092575.633      269374.517
     2092600.182      269563.965     2092599.431      269654.062
     2092574.931      269825.524     2092528.701      270011.934

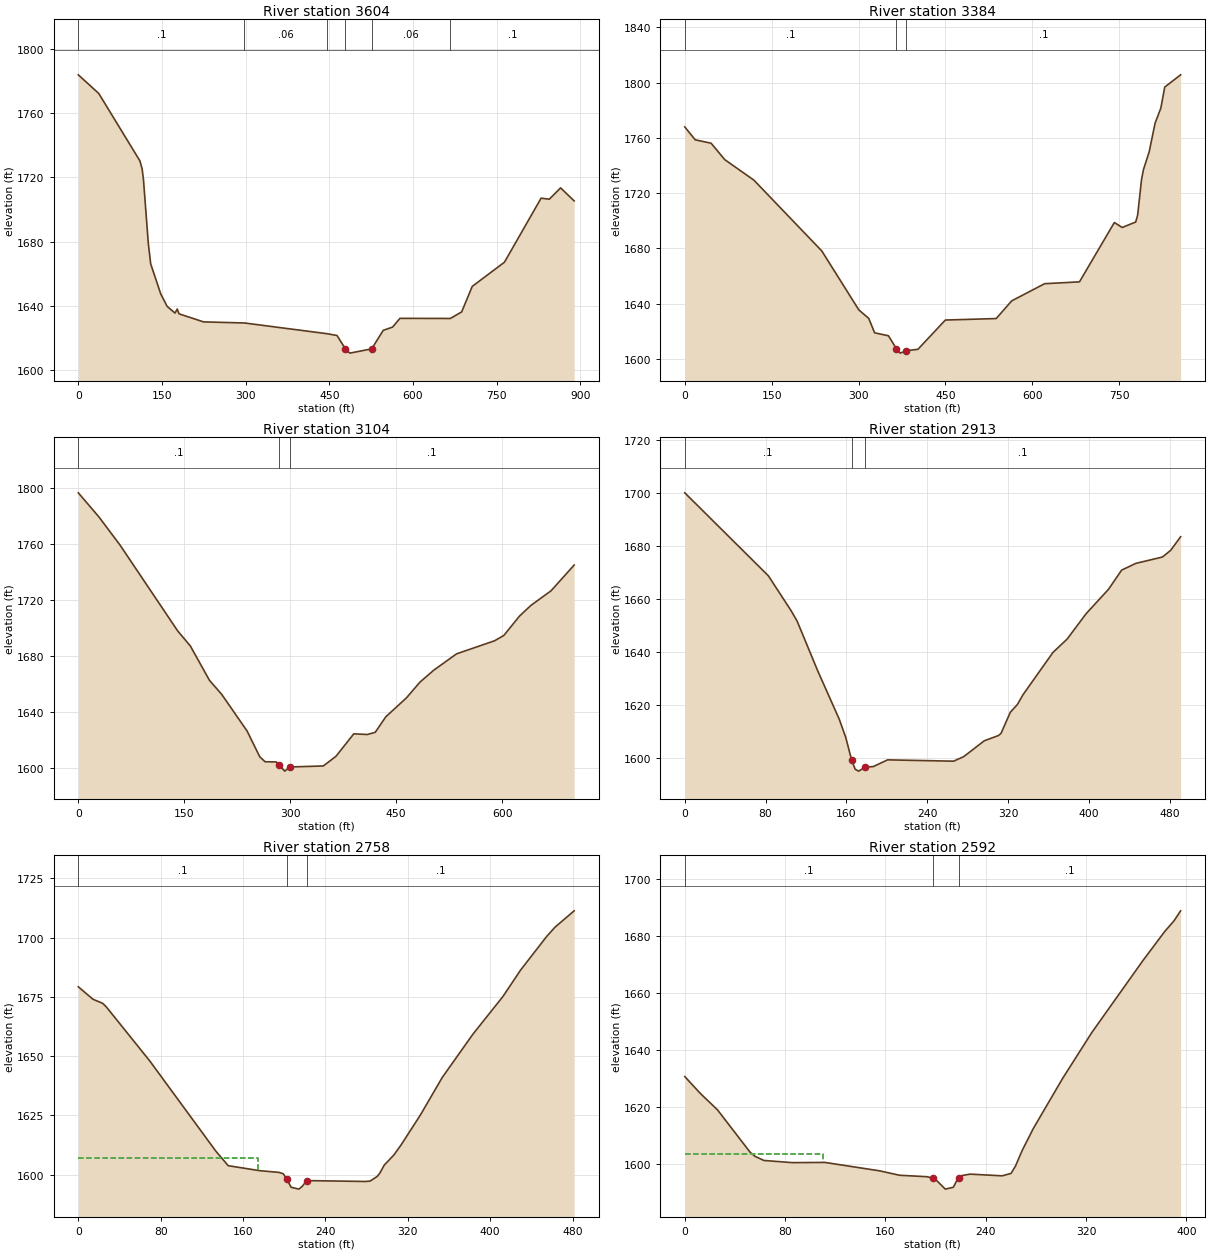
Type RM Length L Ch R = 1 ,3604    ,220.2,220.2,220.2
XS GIS Cut Line= 4
2094012.75103768267220.9728245122094216.57812856267610.282568093
2094257.34354674267842.6454516962094338.87438309 268040.35772985
#Sta/Elev= 30
       0 1783.83    36.7 1772.21   110.4 1730.33   114.4 1725.35   116.8 1718.77
   125.5 1678.99   129.8 1666.21   147.8 1647.54   159.3 1639.79   173.4 1635.61
   177.4 1638.13   180.5 1635.17   224.6 1630.14  297.831629.469  446.111622.786
   463.9 1621.67  479.02 1613.37   486.9 1610.71   526.11613.367   546.8 1624.88
   563.5  1626.9   576.8 1632.34  667.261632.278   687.5 1636.37   706.4 1652.21
   764.2 1667.28   829.9  1707.1   844.6 1706.46   864.9  1713.5   889.2  1705.4
#Mann= 6 ,-1 , 0
       0      .1       0  297.83     .06       0  446.11      .1       0
  479.02    .045       0   526.1     .06       0  667.26      .1       0
Bank Sta=479.02,526.1
XS Rating Curve= 0 ,0
Exp/Cntr(USF)=0,0
Exp/Cntr=0.3,0.1

Type RM Length L Ch R = 1 ,3384    ,279.6,279.6,279.6
XS GIS Cut Line= 4
2093929.18193042267294.3505772292093988.29178678267571.555420826
2094043.32510132267779.4590535232094112.62631222268130.041649837
#Sta/Elev= 30
       0  1767.9      18 1758.58    45.4 1756.13    68.9 1744.28   119.2 1729.45
   236.5 1678.18   300.5  1635.5   317.5 1629.41   327.7 1618.95   351.5 1616.84
  365.091607.617   371.8 1604.27     382 1606.03   402.4 1607.02   449.8 1628.21
   537.5 1629.28   564.3 1642.07   621.1 1654.49   681.3 1655.83   741.5 1698.75
     755 1695.16   778.3  1699.1   781.7 1704.01   788.4 1729.78   791.7 1736.96
   801.7 1750.02   811.8 1770.61   821.8 1781.59   828.5 1796.75   855.9  1805.6
#Mann= 3 ,-1 , 0
       0      .1       0  365.09    .045       0     382      .1       0
Bank Sta=365.09,382
XS Rating Curve= 0 ,0
Exp/Cntr(USF)=0,0
Exp/Cntr=0.3,0.1

Type RM Length L Ch R = 1 ,3104    ,191.3,191.3,191.3
XS GIS Cut Line= 3
2093594.90550138267514.4838353792093815.03875953267850.798535331
2093955.67945224268115.773753476
#Sta/Elev= 30
       0 1796.82    29.2 1779.58    59.2 1759.38   140.6 1698.23   158.6 1687.42
   185.6 1662.93   202.9 1652.93   238.9  1626.7   256.8 1608.33   264.4 1604.73
   280.1 1604.62   284.41602.145   292.2 1598.04   299.7 1601.01   346.8 1601.73
   364.7 1608.62   389.9 1624.67   409.1  1624.2   420.3 1625.76   435.2  1636.8
   464.3 1650.29   483.7 1661.65   503.1 1670.11   535.4  1681.8   589.3 1691.16
   602.3 1694.93   624.5 1708.75   640.6 1716.38   669.1 1726.81   701.9 1745.22
#Mann= 3 ,-1 , 0
       0      .1       0   284.4    .045       0   299.7      .1       0
Bank Sta=284.4,299.7
XS Rating Curve= 0 ,0
Exp/Cntr(USF)=0,0
Exp/Cntr=0.3,0.1

Type RM Length L Ch R = 1 ,2913    ,155,155,155
XS GIS Cut Line= 3
2093474.29151336267752.0291450642093670.47482336267937.380247761
2093802.86846814268114.306300335
#Sta/Elev= 30
       0 1700.03    82.8 1668.72   105.3 1655.55   111.2 1651.67   131.5    1633
     153 1614.59   159.4 1607.74  165.051599.422   168.7 1595.79   172.1 1595.08
   178.9 1596.61   186.5 1596.78   200.8 1599.33   266.1 1598.83   276.2 1600.55
   296.4  1606.5   310.6 1608.51   313.1 1609.33   322.3 1617.29   329.3 1620.21
   334.7 1623.81   364.5 1639.84   378.6  1644.9   397.3 1654.44   419.6 1663.69
   432.5 1670.88   446.6 1673.43   472.9 1675.82   481.1 1678.36   490.9 1683.48
#Mann= 3 ,-1 , 0
       0      .1       0  165.05    .045       0   178.9      .1       0
Bank Sta=165.05,178.9
XS Rating Curve= 0 ,0
Exp/Cntr(USF)=0,0
Exp/Cntr=0.3,0.1

Type RM Length L Ch R = 1 ,2758    ,166.3,166.3,166.3
XS GIS Cut Line= 3
2093334.67639705267894.0514185592093538.08117858268014.409277453
2093712.60007397268186.521015671
#Sta/Elev= 30
       0 1679.21    14.2 1673.96    23.6 1672.25    27.4 1670.62    69.4 1647.92
   133.6 1609.85   145.6 1603.74   176.1 1601.65   195.2  1600.9     199 1600.34
  202.361598.138   206.6 1594.66   214.2 1593.86   217.4 1595.01   221.8 1597.46
   278.7 1597.09   283.3 1597.25   290.3 1599.23   292.7 1600.54   297.1 1604.02
   306.4 1608.25   313.5 1612.56   332.1 1625.07   353.4 1640.96   383.1 1659.18
   412.3  1675.1   429.5 1686.28     455 1700.55     463  1704.4   481.5 1711.26
#Mann= 3 ,-1 , 0
       0      .1       0  202.36    .045       0   221.8      .1       0
#XS Ineff= 2 , 0
          174.03  1606.8
Permanent Ineff=
       F       F
Bank Sta=202.36,221.8
XS Rating Curve= 0 ,0
Exp/Cntr(USF)=0,0
Exp/Cntr=0.3,0.1

Type RM Length L Ch R = 1 ,2592    ,270.9,270.9,270.9
XS GIS Cut Line= 4
2093269.68315324268060.1452638332093426.14836981268144.395765058
2093527.24897128268185.3174370822093624.73883698 268233.46058064
#Sta/Elev= 30
       0  1630.7    12.4 1624.79    26.1 1619.03    52.2 1604.15      56 1602.77
    63.1 1601.32    85.7 1600.56   111.8 1600.63   155.3 1597.69   171.4 1596.13
     193 1595.64  197.911595.146     200 1594.68   207.8 1591.28   214.2 1591.93
   217.7 1594.93  218.421595.146   221.3 1596.06   227.5 1596.53   253.1 1595.94
   260.2 1596.78   263.8 1599.38     269 1604.72     278 1612.51   301.3    1630
   324.6 1646.08   365.4  1671.3   382.8 1681.49   390.3 1685.29   395.5 1688.74
#Mann= 3 ,-1 , 0
       0      .1       0  197.91    .045       0  218.42      .1       0
#XS Ineff= 2 , 0
          110.24 1603.52
Permanent Ineff=
       F       F
Bank Sta=197.91,218.42
XS Rating Curve= 0 ,0
Exp/Cntr(USF)=0,0
Exp/Cntr=0.3,0.1

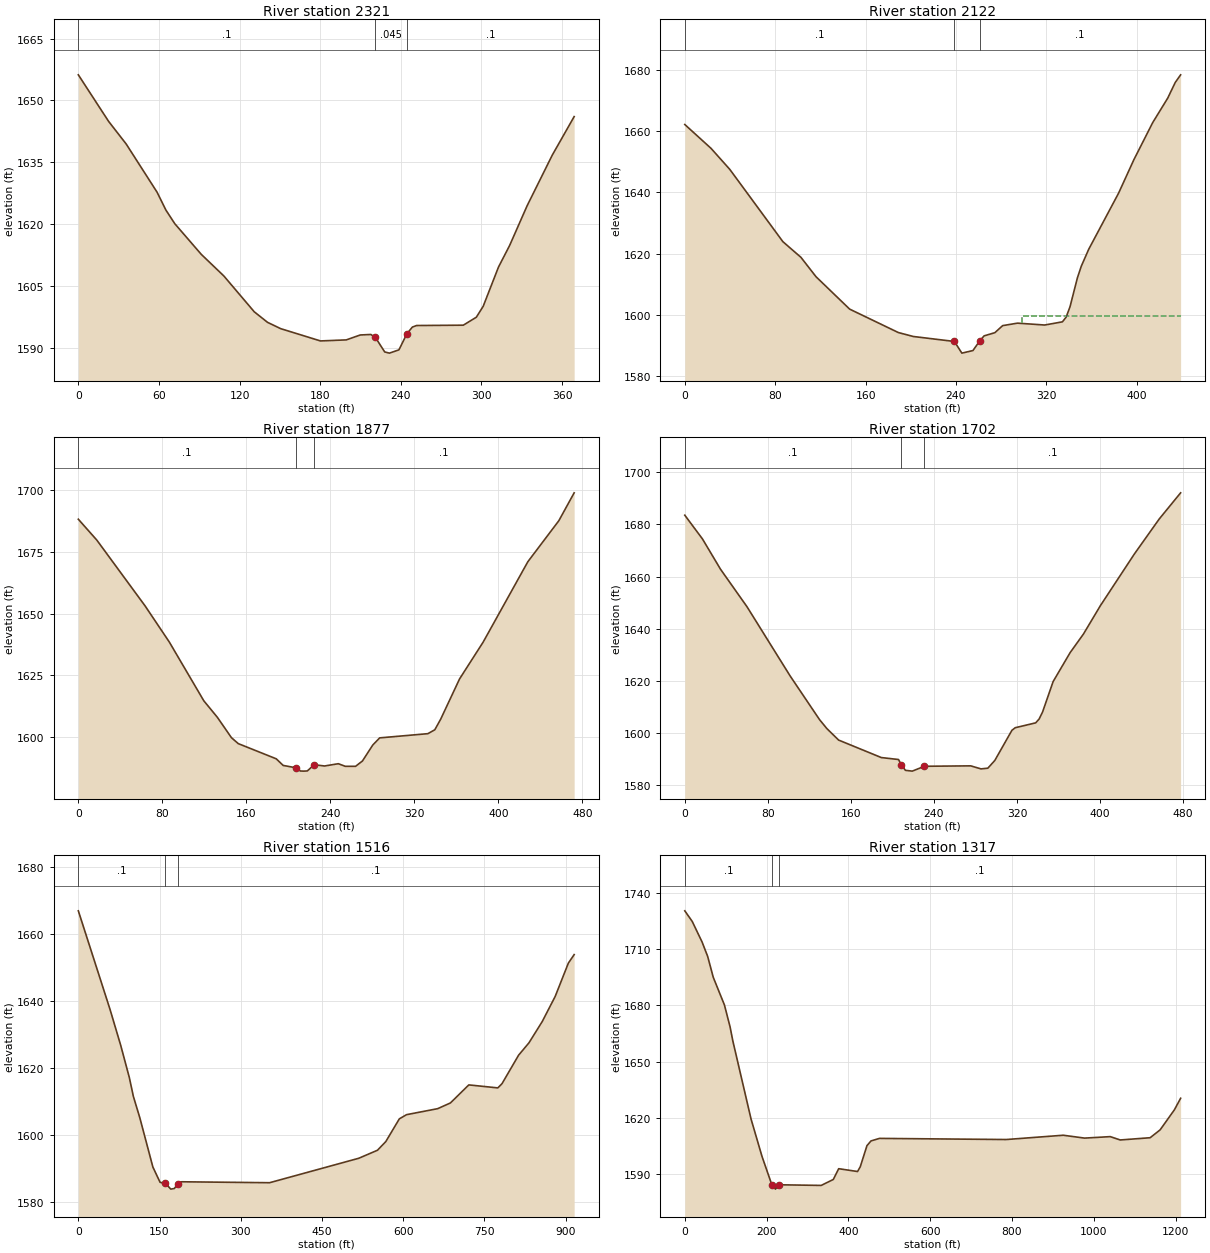
Type RM Length L Ch R = 1 ,2321    ,198.3,198.3,198.3
XS GIS Cut Line= 4
2093227.55790263268447.6975694712093415.31616251 268436.86536217
2093522.43465692 268403.165161682093576.59569342268361.039911067
#Sta/Elev= 30
       0 1656.21    22.5 1644.96    35.6 1639.48    58.6 1627.81    65.2 1623.47
    71.8 1620.18    91.5 1612.77   108.3 1607.54   130.9 1598.88   140.8 1596.32
   150.6 1594.79   180.2 1591.82   199.4 1592.07   209.8 1593.26   217.7 1593.38
   221.1 1592.66     228 1589.16   231.5 1588.87   238.6 1589.66  244.53 1593.56
   248.6 1595.17   251.7 1595.55   286.5 1595.63   296.2 1597.56   301.3  1600.2
   312.7  1609.7     321 1614.93     334 1624.53   352.7 1636.77     369  1646.1
#Mann= 3 ,-1 , 0
       0      .1       0   221.1    .045       0  244.53      .1       0
Bank Sta=221.1,244.53
XS Rating Curve= 0 ,0
Exp/Cntr(USF)=0,0
Exp/Cntr=0.3,0.1

Type RM Length L Ch R = 1 ,2122    ,245.3,245.3,245.3
XS GIS Cut Line= 4
2093233.57579558268651.1023510012093455.03425594  268618.6057291
2093533.26686422  268618.60572912093668.06766618 268595.73773591
#Sta/Elev= 30
       0 1662.17    23.2 1654.39    39.8 1647.53    86.8 1623.91   102.8 1618.78
   116.1 1612.47   145.9 1601.87     189 1594.22   202.3 1592.93   238.6 1591.31
   245.2  1587.5     255 1588.34  261.06 1591.52   264.9 1593.14   274.4 1594.18
   281.3 1596.48   294.4 1597.29   318.5 1596.68   334.2 1597.72   337.5 1599.27
   340.9 1602.64   347.5 1612.14   350.9  1615.9   357.5 1621.45   383.9 1639.75
   397.4 1650.65   414.1  1662.8   427.4  1670.8     434 1675.88   438.8  1678.4
#Mann= 3 ,-1 , 0
       0      .1       0   238.6    .045       0  261.06      .1       0
#XS Ineff= 2 , 0
                          298.53         1599.72
Permanent Ineff=
       F       F
Bank Sta=238.6,261.06
XS Rating Curve= 0 ,0
Exp/Cntr(USF)=0,0
Exp/Cntr=0.3,0.1

Type RM Length L Ch R = 1 ,1877    ,175.4,175.4,175.4
XS GIS Cut Line= 3
2093268.47957465268850.8963967652093517.62034257268864.135761243
2093740.28238152268859.321446888
#Sta/Elev= 30
       0 1688.19    17.6 1679.75    63.6 1653.12    86.6 1638.55   119.5 1614.75
   132.5 1608.02   145.8 1599.84   152.3 1597.43   188.5 1591.28   195.1  1588.6
   207.4 1587.65   211.5 1586.34   214.8  1586.3   218.1 1586.38   224.6 1588.88
   234.5 1588.38   247.6  1589.3   254.2 1588.25     264 1588.24   270.6 1590.41
   280.4 1596.85     287 1599.75   332.9 1601.45   339.5 1603.03   345.1 1607.32
   363.1 1623.62   385.5 1638.46   428.1    1671   457.6 1687.58   472.2 1698.87
#Mann= 3 ,-1 , 0
       0      .1       0   207.4    .045       0   224.6      .1       0
Bank Sta=207.4,224.6
XS Rating Curve= 0 ,0
Exp/Cntr(USF)=0,0
Exp/Cntr=0.3,0.1

Type RM Length L Ch R = 1 ,1702    ,185.7,185.7,185.7
XS GIS Cut Line= 4
2093267.27599607268962.8292055362093435.77699852269030.229606517
2093563.35632894269047.0797067622093730.65375281269039.858235228
#Sta/Elev= 30
       0 1683.56      17 1674.47    34.4 1662.85    59.9 1648.48   101.5 1621.91
   129.8 1605.18   136.9 1601.73   148.2 1597.34   189.3 1590.64   205.9 1589.89
  208.591587.841   212.5 1585.75   219.1 1585.44   230.8  1587.3   275.4 1587.46
   285.3  1586.3   291.9 1586.56   298.6 1589.52   315.1 1601.09   318.3 1602.08
     338 1603.95   341.3 1605.42   344.6 1608.09   354.8 1619.78   371.2 1630.89
     384    1638   400.4 1648.93     433 1668.66     457 1682.11   477.6 1692.14
#Mann= 3 ,-1 , 0
       0      .1       0  208.59    .045       0   230.8      .1       0
Bank Sta=208.59,230.8
XS Rating Curve= 0 ,0
Exp/Cntr(USF)=0,0
Exp/Cntr=0.3,0.1

Type RM Length L Ch R = 1 ,1516    ,186.7,186.7,186.7
XS GIS Cut Line= 5
 2093285.3296749 268992.918670262093362.35870459269107.258636209
2093370.06678003269162.9799682612093550.89509144269398.125444007
2093891.08604553269632.095085415
#Sta/Elev= 30
       0 1666.79    58.6 1637.39    78.4 1626.64    94.2 1617.11   101.7 1611.47
   113.6 1605.11   137.7 1590.44     151 1585.88   160.9 1585.56   170.8 1583.85
   177.4 1584.04   183.8 1585.44   190.7 1586.04   353.3 1585.76   518.1 1593.05
   552.6 1595.44     568 1598.03     593  1604.8   606.3 1606.04   663.8 1607.83
   687.3 1609.53   721.3 1614.91   774.9 1614.02   782.6 1615.27   813.3 1623.77
   832.4 1627.45     857 1633.81   880.9 1641.29   905.2 1651.21   915.9 1653.74
#Mann= 3 ,-1 , 0
       0      .1       0   160.9    .045       0   183.8      .1       0
Bank Sta=160.9,183.8
XS Rating Curve= 0 ,0
Exp/Cntr(USF)=0,0
Exp/Cntr=0.3,0.1

Type RM Length L Ch R = 1 ,1317    ,228,228,228
XS GIS Cut Line= 4
2093117.76878043268955.1151122392093166.52347266269119.662198523
2093190.61159413269405.2873725952093900.89102441269659.010981342
#Sta/Elev= 30
       01730.433  18.2431724.752  42.1961713.848  55.8831706.175   69.571695.017
  96.9451680.231 110.6321668.662 117.4761661.077 161.9591619.474  188.691599.578
   212.81584.419 221.5891582.057 231.4661584.375 333.5331584.031 363.1661587.207
 376.336 1592.95  422.431591.447 429.0151593.934 445.478 1605.24 455.3551607.745
 476.0351609.106   786.1  1608.5 925.4551610.788 977.7131609.2591040.4231610.047
 1064.811608.2631137.9711609.4641162.3591613.6471197.1971624.3211212.4941630.494
#Mann= 3 ,-1 , 0
       0      .1       0   212.8    .045       0 231.466      .1       0
Bank Sta=212.8,231.466
XS Rating Curve= 0 ,0
Exp/Cntr(USF)=0,0
Exp/Cntr=0.3,0.1

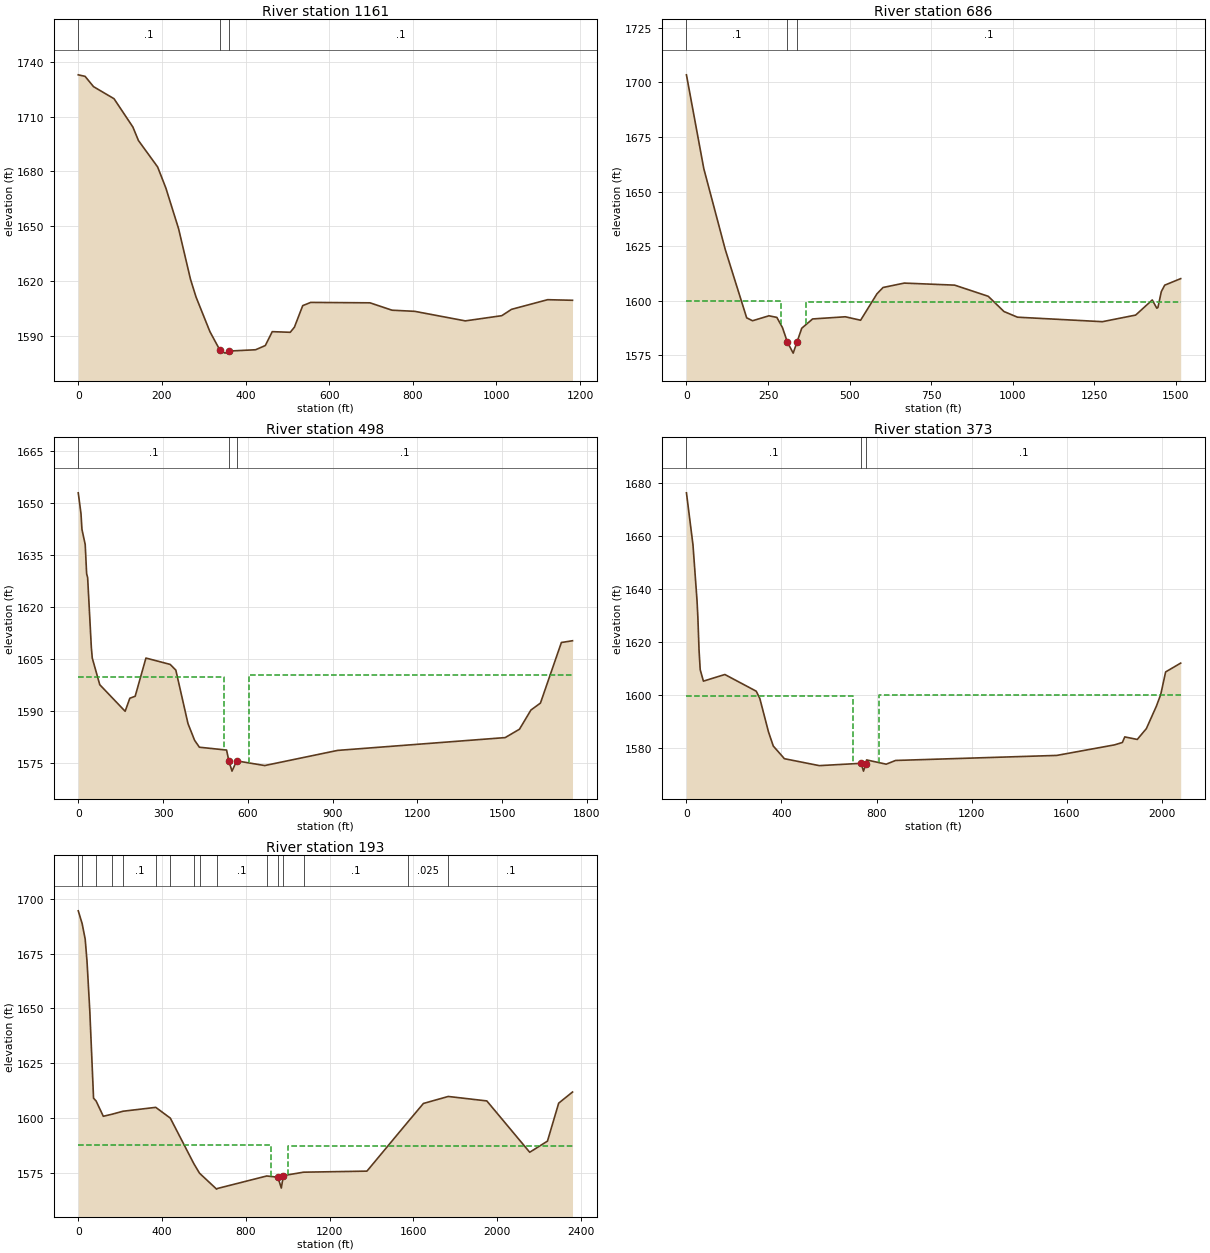
Type RM Length L Ch R = 1 ,1161    ,393.5,393.5,393.5
XS GIS Cut Line= 4
2092806.95761745 268949.020775712093001.94215392269088.731004548
2093044.62818397269389.4131751542093651.02322672269588.926111258
#Sta/Elev= 30
       01732.842   16.311732.012   36.491726.376  85.5581719.766 130.6211704.282
 143.9711696.865 189.862 1682.41 209.4821670.911 239.8711648.676 268.3861620.958
 281.6411611.256 314.7781592.319 339.1541581.981 351.2291580.526  361.17 1581.66
 424.1311582.375 447.3271584.684 463.8961592.275 506.9741591.927 516.9151594.719
 536.7981606.528 555.9971608.287 697.6051608.058 750.3181604.021 804.6741603.397
 925.5591598.1731012.7971601.0211036.0821604.4891122.4281609.7721181.9411609.448
#Mann= 3 , 0 , 0
       0      .1       0 339.154    .045       0  361.17      .1       0
Bank Sta=339.154,361.17
XS Rating Curve= 0 ,0
Exp/Cntr(USF)=0,0
Exp/Cntr=0.5,0.3

Type RM Length L Ch R = 1 ,686     ,209.4,209.4,209.4
XS GIS Cut Line= 6
2092264.56166637269229.3602560452092447.39176224269290.303621335
2092527.28753502269333.281844595 2092611.6935542269337.678216701
2093173.64012567269447.6479545922093716.29233185 269634.31962485
#Sta/Elev= 30
       01703.496  53.1321660.561  118.841623.516 184.5471592.169 202.5431590.828
   252.81593.101 277.051 1592.36 294.2331587.694 309.5171580.948 327.0851575.996
  338.55 1580.94 353.2341587.396 386.5411591.655 486.8331592.649 533.6361591.069
 583.7821603.176 602.4421606.065 667.3591608.081 821.6941607.148 924.7751602.033
 972.9131595.0581014.3851592.458  1274.61590.4031376.3481593.4231427.2591600.344
1441.1371596.5861444.6061596.8791455.0151604.1761465.4241607.133 1514.431610.129
#Mann= 3 ,-1 , 0
       0      .1       0 309.517    .045       0  338.55      .1       0
#XS Ineff= 2 , 0
          290.42 1599.73   367.1         1599.64
Permanent Ineff=
       F       F
Bank Sta=309.517,338.55
XS Rating Curve= 0 ,0
Exp/Cntr(USF)=0,0
Exp/Cntr=0.5,0.3

Type RM Length L Ch R = 1 ,498     ,125.9,125.9,125.9
XS GIS Cut Line= 4
2092052.73349842269465.8997397472092487.13780621269535.009515986
2092980.77906507269473.3043586292093770.60507923269660.888036993
#Sta/Elev= 30
       0 1653.03     9.7 1647.03    13.1 1642.49    24.6 1638.11    29.7 1629.63
    33.2  1628.6    46.3 1608.45    49.6 1605.33    76.1 1597.64   165.9 1589.97
   182.5 1593.73   201.4  1594.3   239.5 1605.33   325.3  1603.5   345.3 1601.85
   388.4  1586.4   411.7 1581.59   428.7 1579.59   524.9 1578.77   533.21575.554
   544.1 1572.69   560.6 1575.65   659.8  1574.3   917.7 1578.67  1510.8 1582.37
  1561.4 1584.79  1601.9 1590.32  1635.6 1592.33  1709.7 1609.82  1749.1 1610.33
#Mann= 3 ,-1 , 0
       0      .1       0   533.2    .045       0   560.6      .1       0
#XS Ineff= 2 , 0
           517.4 1599.86  603.12         1600.32
Permanent Ineff=
       F       F
Bank Sta=533.2,560.6
XS Rating Curve= 0 ,0
Exp/Cntr(USF)=0,0
Exp/Cntr=0.5,0.3

Type RM Length L Ch R = 1 ,373     ,180,180,180
XS GIS Cut Line= 4
2091867.61802636269515.2638656322092489.60601251 269636.20597405
 2093096.7847609269695.4429251132093931.03848835 269752.21166988
#Sta/Elev= 30
       0 1676.12    27.5 1656.55    44.6 1635.44      48 1629.44      53 1616.95
      58 1609.44    71.4 1605.16   161.6 1607.66   293.7 1601.37   308.7 1598.65
   345.4    1586   365.5  1580.7   412.3 1575.93   559.1 1573.32   735.1 1574.19
     745 1571.25   754.8 1573.82   758.1 1575.47   840.6 1573.87   880.1 1575.27
  1558.4 1577.17  1801.3 1581.14  1834.6 1582.05  1844.5 1584.15  1897.1 1583.19
  1935.4 1587.27  1977.7 1595.75  1995.8 1600.12  2016.5 1608.63  2079.9 1611.96
#Mann= 3 ,-1 , 0
       0      .1       0   735.1    .045       0   754.8      .1       0
#XS Ineff= 2 , 0
           701.3 1599.73  811.69            1600
Permanent Ineff=
       F       F
Bank Sta=735.1,754.8
XS Rating Curve= 0 ,0
Exp/Cntr(USF)=0,0
Exp/Cntr=0.5,0.3

Type RM Length L Ch R = 1 ,193     ,,,
XS GIS Cut Line= 4
2091655.35228505269581.905435577 2092279.8084775269796.639383177
2092943.75597065269860.8127468282093972.99799536269789.234764294
#Sta/Elev= 30
       0 1694.48   18.551688.672    33.1 1681.56    41.8  1671.5    55.1  1648.9
      73 1609.04   85.251607.737   119.6 1600.78  161.061601.708  213.93 1603.08
  369.891604.843  439.331599.944  552.031579.108  578.721574.829   660.3 1567.55
  664.351567.842   899.51573.544   952.8 1572.99   969.2 1568.05   979.1 1573.72
 1075.191575.276  1377.9 1575.76 1575.091598.399  1647.4 1606.62 1766.061609.814
  1950.1 1607.78  2154.8 1584.37  2239.5 1589.44  2293.1 1606.76  2359.1 1611.84
#Mann= 16 ,-1 , 0
       0      .1       0   18.55      .1       0   85.25      .1       0
  161.06    .055       0  213.93      .1       0  369.89    .025       0
  439.33      .1       0  552.03    .055       0  578.72    .025       0
  664.35      .1       0   899.5    .025       0   952.8    .045       0
   979.1    .055       0 1075.19      .1       0 1575.09    .025       0
 1766.06      .1       0
#XS Ineff= 2 , 0
          922.08 1587.75    1000         1587.43
Permanent Ineff=
       F       F
Bank Sta=952.8,979.1
XS Rating Curve= 0 ,0
Exp/Cntr(USF)=0,0
Exp/Cntr=0.5,0.3
Stream Node=ANGLINSCK       ,Main            , 0 , 0 ,Upstream end
Stream Node=ANGLINSCK       ,Main            , 0 , 1 ,Downstream end
Stream Node=GRBRRVTR1       ,Main            , 0 , 0 ,Upstream end
Stream Node=GRBRRVTR1       ,Main            , 0 , 1 ,Downstream end
Stream Node=GRBRRVTR2       ,Main            , 0 , 0 ,Upstream end
Stream Node=GRBRRVTR2       ,Main            , 0 , 1 ,Downstream end
Stream Node=GRBRRVTR4       ,Main            , 0 , 0 ,Upstream end
Stream Node=GRBRRVTR4       ,Main            , 0 , 1 ,Downstream end
Stream Node=HOMINYCK        ,Main            , 0 , 0 ,Upstream end
Stream Node=HOMINYCK        ,Main            , 0 , 1 ,Downstream end
Stream Node=HOWARDCK        ,Main            , 0 , 0 ,Upstream end
Stream Node=HOWARDCK        ,Main            , 0 , 1 ,Downstream end
Stream Node=JERCHODFT       ,Main            , 0 , 0 ,Upstream end
Stream Node=JERCHODFT       ,Main            , 0 , 1 ,Downstream end
Stream Node=JERCHODFTT1     ,Main            , 0 , 0 ,Upstream end
Stream Node=JERCHODFTT1     ,Main            , 0 , 1 ,Downstream end
Stream Node=LITTLECK2       ,Main            , 0 , 0 ,Upstream end
Stream Node=LITTLECK2       ,Main            , 0 , 1 ,Downstream end
Stream Node=SLPHRLCKRN      ,Main            , 0 , 0 ,Upstream end
Stream Node=SLPHRLCKRN      ,Main            , 0 , 1 ,Downstream end
Stream Node=SLSHLCKRN       ,Main            , 0 , 0 ,Upstream end
Stream Node=SLSHLCKRN       ,Main            , 0 , 1 ,Downstream end
Stream Node=YOUNGSCK        ,Main            , 0 , 0 ,Upstream end
Stream Node=YOUNGSCK        ,Main            , 0 , 1 ,Downstream end
LCMann Table=0

Chan Stop Cuts=-1
Use User Specified Reach Order=0
Composite Channel Slope=5